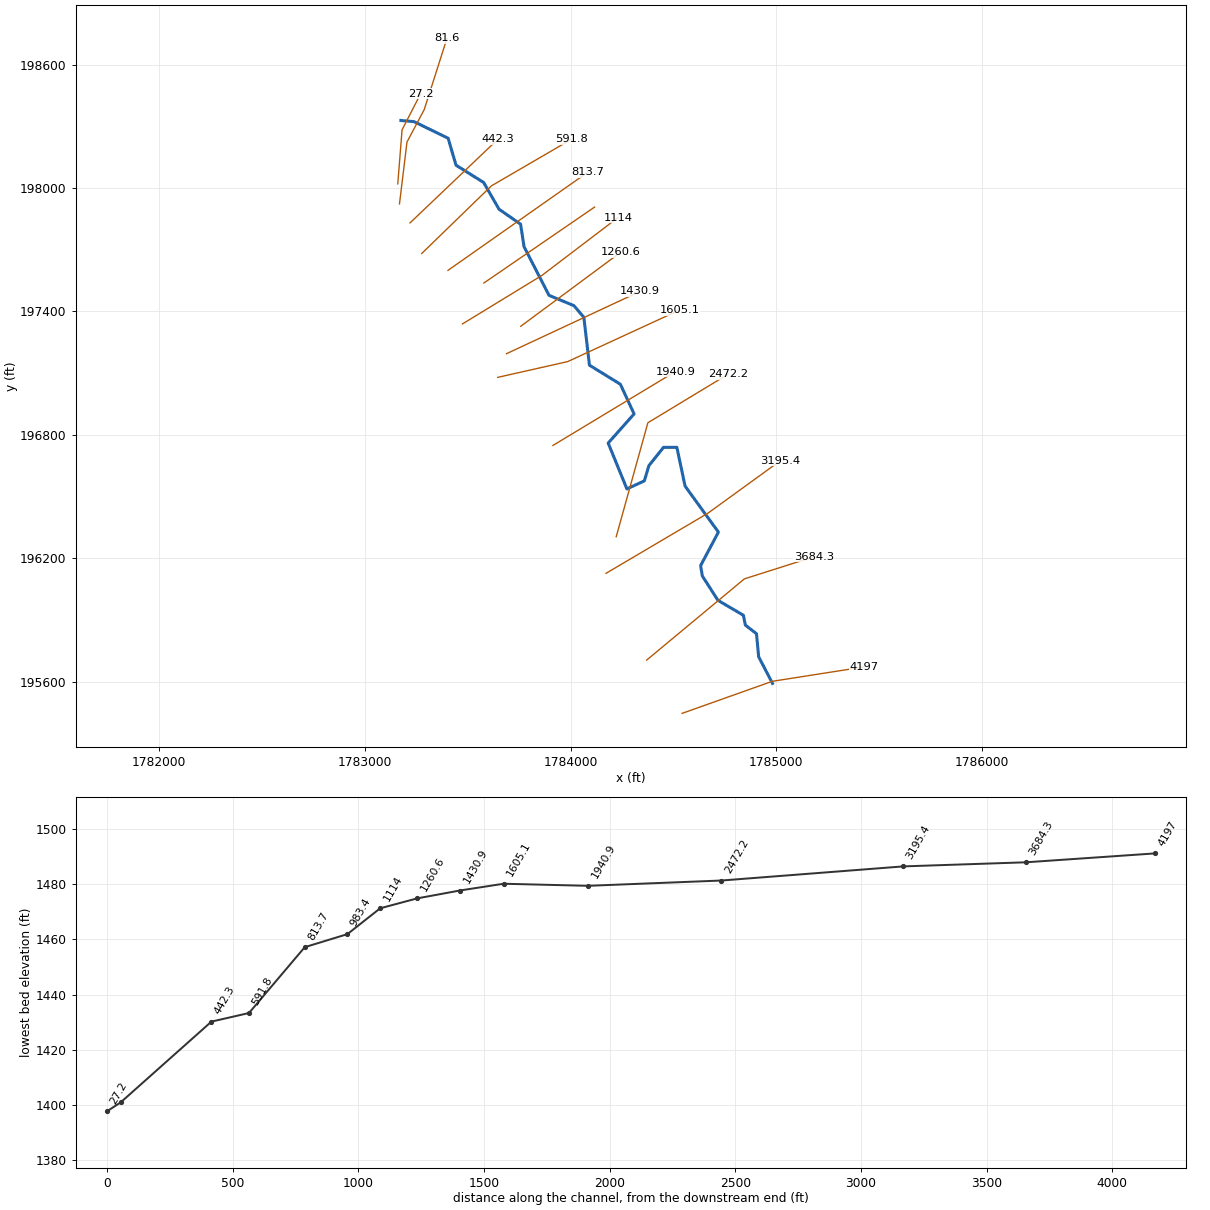
--- MarchFk.prj (project) ---

Proj Title=MarchFk
Current Plan=p01
Default Exp/Contr=0,0
English Units
Geom File=g01
Flow File=f01
Plan File=p01
BEGIN DESCRIPTION:
END DESCRIPTION:
DSS Export Rating Curves= 0
DSS Export Rating Curve Sorted= 0
DSS Export Volume Flow Curves= 0
DXF OffsetX= 0
DXF OffsetY= 0
DXF ScaleX= 0
DXF ScaleY= 0

--- MarchFk.p01 (plan) ---

Plan Title=Floodplain
Program Version=4.00
Geom File=g01
Flow File=f01
K Sum by GR=0
Std Step Tol=0.01
Critical Tol=0.01
Num of Std Step Trials=20
Max Error Tol=0.3
Flow Tol Ratio=0.001
Split Flow NTrial=30
Split Flow Tol=0.02
Split Flow Ratio=0.02
Log Output Level=0
Friction Slope Method=1
Unsteady Friction Slope Method=2
Unsteady Bridges Friction Slope Method=1
Global Log Level=0
CheckData=False
Run HTab=0
Run UNet=0
Run PostProcess=0
UNET Theta=0
UNET Theta Warmup=0
UNET ZTol=0
UNET ZSATol=0
UNET MxIter=0
UNET MaxInSteps=0
UNET DtIC=0
UNET DtMin=0
UNET MaxCRTS=0
UNET WFStab=0
UNET SFStab=0
UNET WFX=0
UNET SFX=0
UNET DSS MLevel=0
UNET DZMax Abort=0
UNET Convert EG Bridges=0
UNET Use Existing IB Tables=0
UNET Froude Limit=0
UNET Froude Power=0
Write IC File=0
Echo Input=False
Echo Output=False
Write Detailed=0

--- MarchFk.f01 (steady flow) ---

Flow Title=NFF Regression Equation
Program Version=4.00
Number of Profiles=1
Profile Names=P100yr
River Rch & RM=MarchFk,Main      ,4197
520.3703
River Rch & RM=MarchFk,Main      ,3684.3
578.4703
River Rch & RM=MarchFk,Main      ,2472.2
615.5653
River Rch & RM=MarchFk,Main      ,81.6
660.9362
Boundary for River Rch & Prof#=MarchFk,Main      ,1
Up Type=0
Dn Type=3
Dn Slope=0.056224

--- MarchFk.g01 (geometry) ---

Geom Title=USGS 10m DEM
Program Version=4.00

River Reach=MarchFk         ,Main
Reach XY= 30
     1784980.942      195591.872     1784913.748      195721.224
     1784903.222      195833.295     1784849.215      195875.044
     1784839.629      195922.978       1784715.8      195995.678
     1784639.904      196113.914     1784631.624      196164.645
     1784718.087      196327.401      1784556.02      196550.911
     1784516.075      196739.451     1784451.364      196739.451
     1784380.262      196650.773     1784357.893      196576.476
      1784273.21       196537.33     1784182.136      196760.222
     1784308.191      196901.999     1784241.319      197046.268
     1784091.062        197138.9     1784063.899      197371.379
     1784015.965      197428.101     1783894.533      197478.431
     1783773.101      197714.905     1783756.324      197824.354
     1783651.668      197897.053     1783576.572      198027.274
     1783442.357      198111.158      1783404.01      198242.177
     1783238.638      198322.866     1783174.261      198328.719

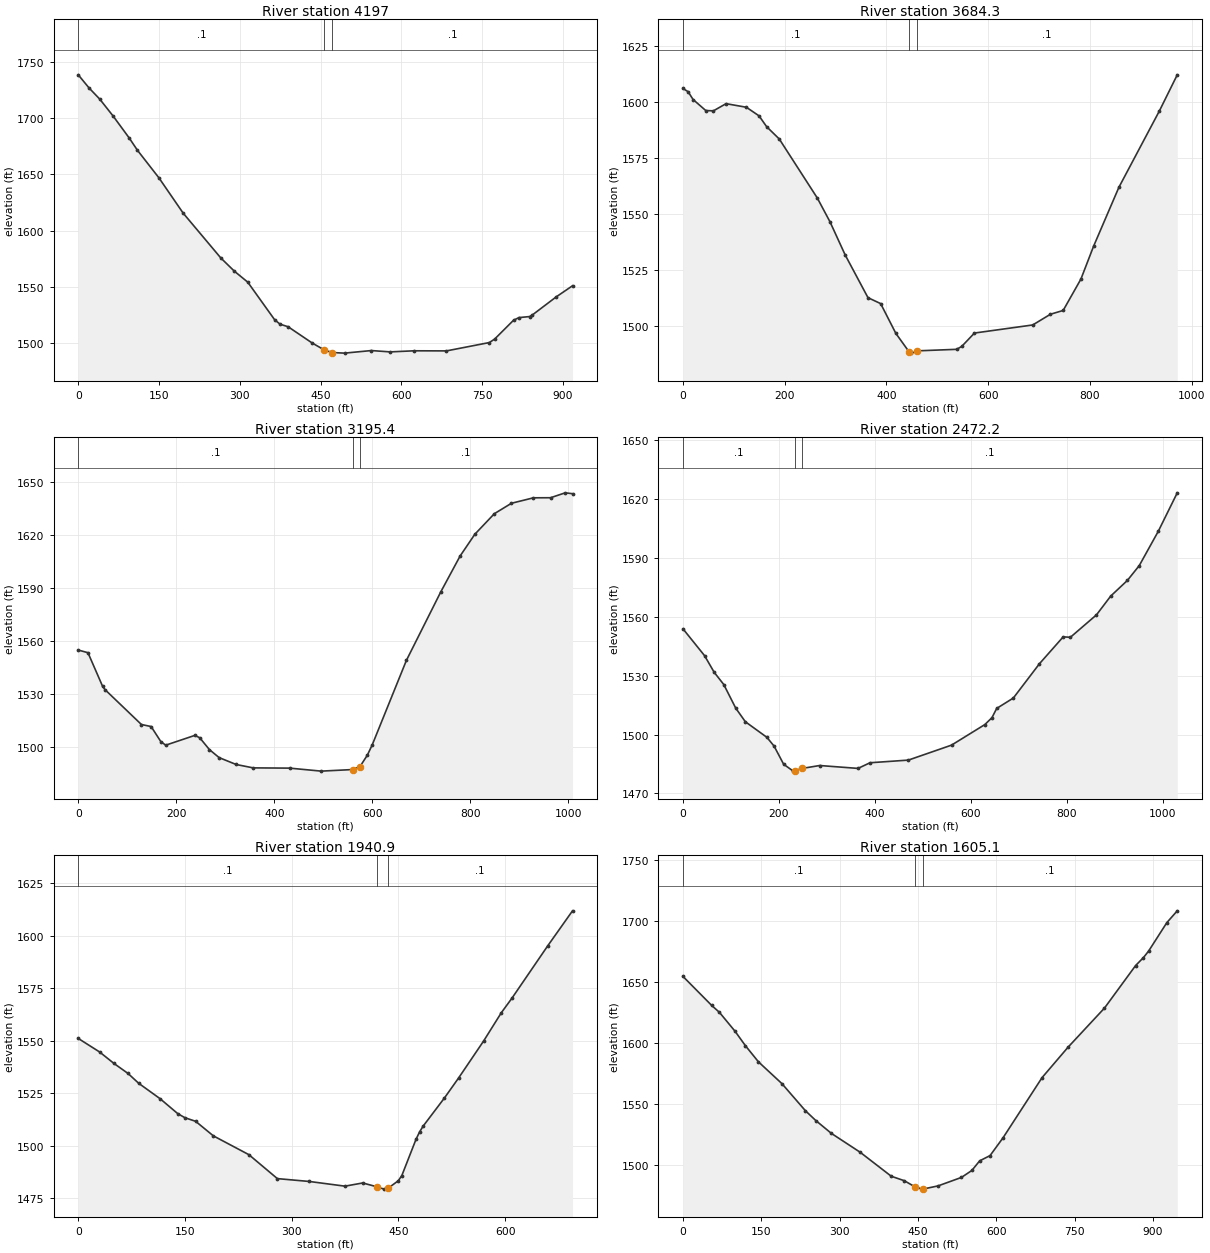
Type RM Length L Ch R = 1 ,4197    ,503.4,512.7,525.7
XS GIS Cut Line= 3
     1784541.563      195446.024     1784979.391      195601.751
     1785427.196      195672.049
#Sta/Elev= 30
       0 1738.32      20 1726.69      40 1716.71      65 1701.57    94.9 1682.06
   109.9 1671.35   149.9  1646.8   194.9 1615.48   264.8 1575.69   289.8 1564.03
   314.8 1554.23   364.8 1520.81   374.8 1516.91   389.8 1514.62   434.7 1500.12
   457.2 1493.97   472.2 1491.71   494.6  1491.2   544.4 1493.48   579.3  1492.3
   624.1 1493.27   683.9 1493.18   763.6  1500.6   773.5 1503.73   808.4 1520.37
   818.4 1522.74   838.3 1523.67   843.3 1525.05   888.1 1541.27     918 1551.01
#Mann= 3 , 0 , 0
       0      .1       0   457.2    .045       0   472.2      .1       0
Bank Sta=457.2,472.2
XS Rating Curve= 0 ,0
Exp/Cntr=0.3,0.1

Type RM Length L Ch R = 1 ,3684.3  ,492.5,489,486.8
XS GIS Cut Line= 3
     1784369.266      195705.079     1784844.394       196099.97
     1785181.653      196207.165
#Sta/Elev= 30
       0 1606.07      10 1604.65    19.9 1601.14    44.8 1596.23    59.8  1596.1
    84.7  1599.3   124.6  1597.7   149.5 1593.86   164.4 1589.04   189.3 1583.53
   264.1 1557.18     289 1546.58   318.9 1531.77   363.7 1512.72   388.6 1510.08
   418.5 1496.78   445.3  1488.3   448.4 1487.98   460.3 1488.99   538.1 1489.68
     548 1490.98     573 1496.94   687.6 1500.55   722.5 1505.34   747.4 1507.02
   782.3 1521.02   807.2 1535.67     857 1561.99   936.8 1596.15   971.7 1612.17
#Mann= 3 , 0 , 0
       0      .1       0   445.3    .045       0   460.3      .1       0
Bank Sta=445.3,460.3
XS Rating Curve= 0 ,0
Exp/Cntr=0.3,0.1

Type RM Length L Ch R = 1 ,3195.4  ,705.2,723.2,735.4
XS GIS Cut Line= 3
     1784171.926      196127.092     1784667.213      196419.341
     1785018.378      196673.759
#Sta/Elev= 30
       0 1555.01    19.8 1553.52    49.6 1534.54    54.5 1532.64   128.9 1512.88
   148.7 1511.73   168.6 1503.18   178.5 1501.18     238 1506.72   247.9 1505.38
   267.7 1498.67   287.5 1494.14   322.2 1490.25     357 1488.33   431.3 1488.19
   495.8 1486.49   559.9 1487.38   574.9 1489.04     590 1495.53     600 1501.37
   669.8 1549.23   739.6  1587.8   779.4 1608.28   809.4 1620.56   849.2 1632.19
   884.1 1638.09     929 1641.18   963.9 1641.22   993.8    1644  1008.7 1643.51
#Mann= 3 , 0 , 0
       0      .1       0   559.9    .045       0   574.9      .1       0
Bank Sta=559.9,574.9
XS Rating Curve= 0 ,0
Exp/Cntr=0.3,0.1

Type RM Length L Ch R = 1 ,2472.2  ,548.8,531.3,512.8
XS GIS Cut Line= 3
      1784221.32      196305.097     1784375.166       196858.94
     1784764.907      197094.836
#Sta/Elev= 30
       0 1553.91      45 1540.23      65 1531.76      85 1525.53     110 1513.46
     130 1506.55   174.9  1498.6   189.9 1494.13   209.9 1484.85   229.9 1481.37
     233 1481.49     248 1482.73   284.9 1484.23   364.9 1482.76   389.9 1485.64
   469.8 1486.99   559.8 1494.62   629.3 1505.11   644.1 1508.62     654 1513.34
   688.7 1518.64   743.2 1536.15   792.7 1549.84   807.6  1549.6     862 1561.04
   891.7 1570.62   926.4 1578.59   951.2 1586.16   990.8 1603.62  1030.4 1623.26
#Mann= 3 , 0 , 0
       0      .1       0     233    .045       0     248      .1       0
Bank Sta=233,248
XS Rating Curve= 0 ,0
Exp/Cntr=0.3,0.1

Type RM Length L Ch R = 1 ,1940.9  ,338.8,335.7,333
XS GIS Cut Line= 2
      1783913.63      196748.684     1784508.498      197107.657
#Sta/Elev= 30
       0 1551.12      30 1544.69      50 1539.28      70 1534.46      85 1529.78
     115 1522.47     140 1515.32     150 1513.41     165 1511.71   189.9 1504.79
   239.9 1495.83   279.9 1484.45   324.9 1483.09   374.9 1480.86   399.9 1482.38
   420.2 1480.53   429.9 1479.45   435.2 1479.78   449.9 1483.44   454.9 1485.92
   474.8 1503.14   479.8 1506.64   484.8 1509.41   514.8 1522.82   534.8 1532.38
   569.8 1549.88   594.8 1563.39   609.8 1570.34   659.8 1595.09   694.8 1611.82
#Mann= 3 , 0 , 0
       0      .1       0   420.2    .045       0   435.2      .1       0
Bank Sta=420.2,435.2
XS Rating Curve= 0 ,0
Exp/Cntr=0.3,0.1

Type RM Length L Ch R = 1 ,1605.1  ,174,174.2,174
XS GIS Cut Line= 3
     1783644.892      197079.619     1783985.424      197156.374
      1784528.05      197406.501
#Sta/Elev= 30
       0 1654.73    54.8    1631    69.8 1625.25    99.7 1609.74   119.7 1597.81
   144.6 1584.61   189.5 1566.76   234.4 1544.56   254.3 1536.51   284.2 1525.94
   339.1 1510.53   398.9 1490.76   423.8 1487.12   444.6    1482   458.6  1480.2
   459.6 1480.25   488.5 1482.85   533.3 1489.81   553.2 1495.51   568.2 1503.41
   588.1 1507.72     613 1522.35   687.7 1571.71   737.4 1596.63   807.2 1628.75
   866.9 1663.69   881.8 1670.17   891.8 1675.57   926.7  1698.9   946.6 1708.57
#Mann= 3 , 0 , 0
       0      .1       0   444.6    .045       0   459.6      .1       0
Bank Sta=444.6,459.6
XS Rating Curve= 0 ,0
Exp/Cntr=0.3,0.1

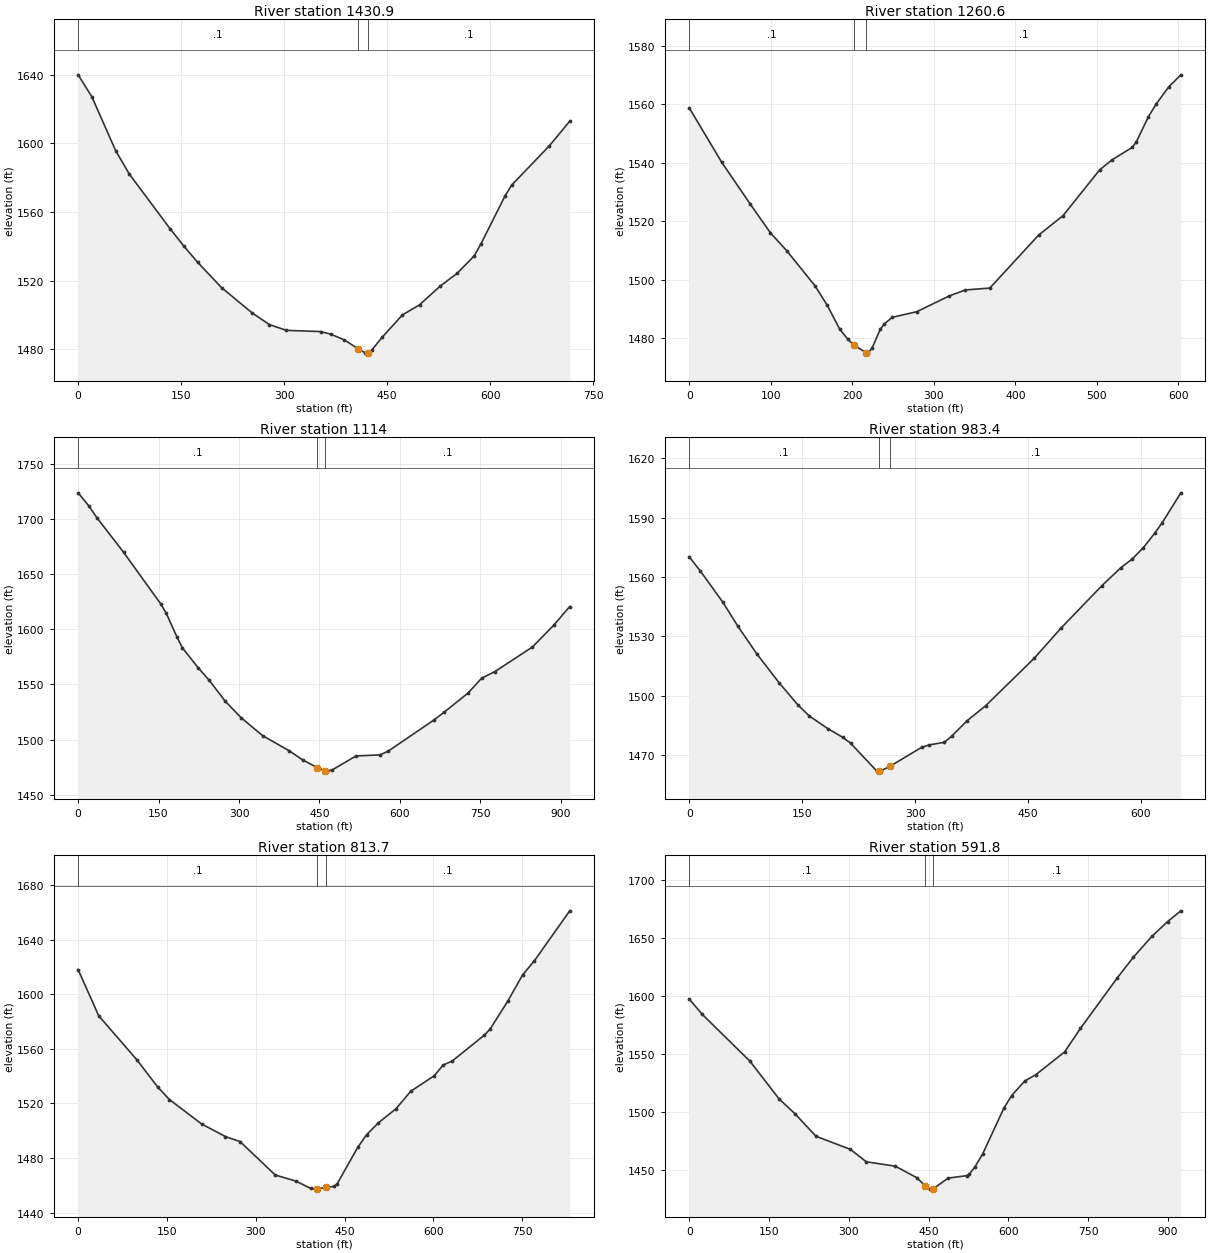
Type RM Length L Ch R = 1 ,1430.9  ,165.9,170.3,174.7
XS GIS Cut Line= 2
      1783687.99      197194.836     1784336.704      197497.398
#Sta/Elev= 30
       0 1639.98    19.9 1627.27    54.7 1595.74    74.6  1582.1   134.2 1550.11
   154.1 1540.04     174 1530.72   208.8 1515.95   253.5 1501.15   278.4  1494.4
   303.2 1491.03   352.9 1490.32   367.8  1488.8   387.7 1485.44   407.4 1480.33
   417.6 1478.01   422.4 1477.76   422.5 1477.75   427.5 1479.46   442.4  1486.9
   472.2 1500.03   497.1 1505.92   526.9 1516.74   551.8 1524.27   576.6 1534.41
   586.6 1541.51   621.4 1569.28   631.3 1575.73     686 1598.55   715.8 1612.97
#Mann= 3 , 0 , 0
       0      .1       0   407.4    .045       0   422.4      .1       0
Bank Sta=407.4,422.4
XS Rating Curve= 0 ,0
Exp/Cntr=0.3,0.1

Type RM Length L Ch R = 1 ,1260.6  ,148.2,146.7,147.4
XS GIS Cut Line= 2
      1783757.22      197328.168     1784241.833      197687.141
#Sta/Elev= 30
       0 1558.77    39.9 1540.14    74.8 1525.89    99.7    1516   119.6 1509.91
   154.5 1497.83   169.5 1491.17   184.4 1483.18   194.4 1479.68   202.3 1477.59
   217.3    1475   219.3 1474.88   224.3 1476.58   234.3 1482.99   239.2 1484.84
   249.2 1487.14   279.1 1489.04     319 1494.44   338.9 1496.49   368.8 1497.13
   428.6 1515.24   458.5 1521.87   503.4 1537.51   518.4 1540.92   543.3 1545.21
   548.3 1547.03   563.2 1555.65   573.2  1560.2   588.1 1565.88   603.1 1570.05
#Mann= 3 , 0 , 0
       0      .1       0   202.3    .045       0   217.3      .1       0
Bank Sta=202.3,217.3
XS Rating Curve= 0 ,0
Exp/Cntr=0.3,0.1

Type RM Length L Ch R = 1 ,1114    ,129.3,130.5,129.4
XS GIS Cut Line= 3
     1783473.772      197339.546     1783860.854      197575.906
     1784229.516      197856.457
#Sta/Elev= 30
       0 1723.93    19.9  1712.1    34.9  1701.4    84.7    1670   154.5  1622.8
   164.5 1614.41   184.4 1592.98   194.4 1583.23   224.3 1564.86   244.2 1553.93
   274.1  1534.9     304 1519.79   343.9 1503.56   393.7 1489.77   418.6 1481.54
     446 1474.44     461  1471.6   463.5  1471.3   473.5 1472.32   518.3 1485.09
   563.1 1486.06   578.1 1489.39   662.8 1517.48   682.7 1524.84   727.5 1542.33
   752.4 1555.63   777.3  1561.7   847.1 1583.95   886.9 1603.74   916.8 1620.72
#Mann= 3 , 0 , 0
       0      .1       0     446    .045       0     461      .1       0
Bank Sta=446,461
XS Rating Curve= 0 ,0
Exp/Cntr=0.3,0.1

Type RM Length L Ch R = 1 ,983.4   ,170.2,169.7,169.6
XS GIS Cut Line= 2
     1783577.734      197538.424     1784116.193      197907.652
#Sta/Elev= 30
       0 1570.19      15 1562.94    44.9 1547.13    64.8 1535.05    89.7 1521.22
   119.6 1506.48   144.5 1495.32   159.5 1489.79   184.4 1483.33   204.3 1478.92
   214.3 1476.04   249.2 1461.93   251.8 1461.96   254.2 1461.99   266.8  1464.4
     309 1474.03     319 1475.18   338.9 1476.52   348.9 1479.71   368.8 1487.32
   393.7 1494.96   458.5 1519.06   493.4 1534.03   548.2 1555.68   573.2 1564.67
   588.1 1569.01     603 1574.78     618 1582.02     628 1587.33   652.9 1602.52
#Mann= 3 , 0 , 0
       0      .1       0   251.8    .045       0   266.8      .1       0
Bank Sta=251.8,266.8
XS Rating Curve= 0 ,0
Exp/Cntr=0.3,0.1

Type RM Length L Ch R = 1 ,813.7   ,218.2,221.9,224.7
XS GIS Cut Line= 2
     1783403.376      197599.962      1784082.86      198076.882
#Sta/Elev= 30
       0 1618.05    34.8 1584.17    99.4 1551.83   134.2 1532.12   154.1 1522.85
   208.8 1504.88   248.6 1495.73   273.4 1492.06     333  1467.5   367.8 1463.09
   392.7  1457.7   402.6  1457.2   403.1 1457.23   418.1 1458.54   432.5 1459.18
   437.4 1461.07   472.2 1487.82   487.2 1497.09     507 1505.76   536.9 1516.14
   561.7 1528.91   601.5 1540.29   616.4 1548.11   631.3 1550.92     686    1570
   695.9  1574.6   725.8 1595.12   750.6 1614.15   770.5 1624.53   830.2 1661.09
#Mann= 3 , 0 , 0
       0      .1       0   403.1    .045       0   418.1      .1       0
Bank Sta=403.1,418.1
XS Rating Curve= 0 ,0
Exp/Cntr=0.3,0.1

Type RM Length L Ch R = 1 ,591.8   ,149.6,149.5,149.9
XS GIS Cut Line= 3
     1783275.725      197681.941      1783614.34      198010.663
     1784004.991      198238.056
#Sta/Elev= 30
       0 1597.34    24.8    1584   114.3 1543.65   168.9 1511.18   198.7  1498.4
   238.4  1478.9     303 1467.61   332.8 1456.92   387.5  1453.1   427.2 1443.32
   443.5  1436.3   452.1 1433.35     457 1433.33   458.5 1433.66   486.8 1442.87
   521.6 1444.94   526.6 1446.43   536.5 1452.22   551.4 1463.59   591.1 1502.97
     606 1514.09   630.9 1526.76   650.8 1531.86   705.4 1551.65   735.2 1571.96
   804.7  1615.7   834.5 1633.31   869.3 1651.34   899.1 1664.18   923.9 1673.43
#Mann= 3 , 0 , 0
       0      .1       0   443.5    .045       0   458.5      .1       0
Bank Sta=443.5,458.5
XS Rating Curve= 0 ,0
Exp/Cntr=0.3,0.1

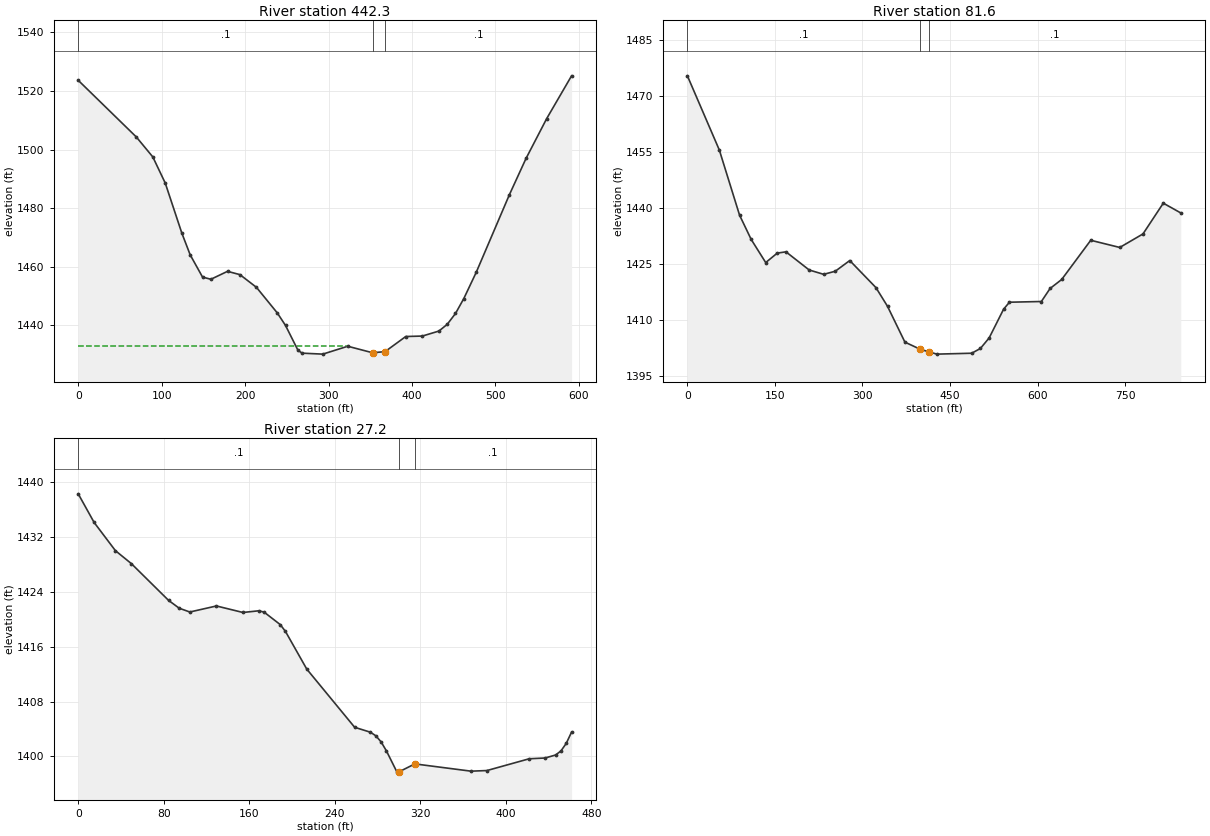
Type RM Length L Ch R = 1 ,442.3   ,353.9,360.8,367.7
XS GIS Cut Line= 2
     1783218.762       197830.73     1783646.964       198238.42
#Sta/Elev= 30
       0 1523.66    69.6 1504.33    89.4 1497.51   104.3 1488.59   124.2 1471.49
   134.2 1464.08     149  1456.5     159 1455.76   178.9 1458.46   193.8 1457.34
   213.6    1453   238.5 1444.29   248.4 1440.01   263.3 1431.55   268.3 1430.54
   293.1 1430.21     323  1432.9   352.7 1430.68   367.7 1431.06   392.5 1436.22
   412.4 1436.38   432.2 1438.08   442.2 1440.38   452.1 1444.08   462.1 1449.19
     477 1458.16   516.7 1484.62   536.6 1496.98   561.4  1510.6   591.2 1525.19
#Mann= 3 , 0 , 0
       0      .1       0   352.7    .045       0   367.7      .1       0
#XS Ineff= 2 , 0
          322.59 1432.98
Permanent Ineff=
       F       F
Bank Sta=352.7,367.7
XS Rating Curve= 0 ,0
Exp/Cntr=0.3,0.1

Type RM Length L Ch R = 1 ,81.6    ,54.9,54.3,53.8
XS GIS Cut Line= 4
      1783167.48      197923.037      1783203.96      198223.926
     1783287.992      198382.009     1783398.335      198728.018
#Sta/Elev= 30
       0 1475.41    54.7 1455.57    89.4 1438.13   109.3 1431.64   134.2 1425.45
     154 1427.98   168.9 1428.32   208.7 1423.46   233.5  1422.3   253.4 1423.13
   278.2 1425.99     323 1418.76   342.9 1413.74   372.7 1404.16   399.2 1402.23
   414.2 1401.55   427.4 1400.95   487.1 1401.19     502 1402.46     517 1405.28
   541.8 1412.98   551.8 1414.84   606.5 1415.03   621.4 1418.51   641.3 1420.92
   691.1 1431.41   740.8 1429.49   780.6 1433.11   815.4 1441.34   845.3 1438.73
#Mann= 3 , 0 , 0
       0      .1       0   399.2    .045       0   414.2      .1       0
Bank Sta=399.2,414.2
XS Rating Curve= 0 ,0
Exp/Cntr=0.3,0.1

Type RM Length L Ch R = 1 ,27.2    ,24.4,27.2,30
XS GIS Cut Line= 3
     1783159.149      198020.465     1783180.089      198283.161
     1783270.509      198459.243
#Sta/Elev= 30
       0 1438.32    14.9 1434.14    34.8 1430.03    49.7 1428.14    84.5 1422.78
    94.5 1421.63   104.4 1421.08   129.3 1421.96   154.1 1421.01   169.1 1421.26
     174 1421.05     189 1419.24   193.9 1418.24   213.8 1412.75   258.6 1404.26
   273.4 1403.54   278.4 1403.02   283.3 1402.14   288.3 1400.82   298.2 1397.72
   299.9 1397.75   314.9 1398.92   367.4 1397.86   382.3 1397.95   421.9 1399.67
   436.7 1399.78   446.6 1400.22   451.6 1400.82   456.5 1401.91   461.5 1403.56
#Mann= 3 , 0 , 0
       0      .1       0   299.9    .045       0   314.9      .1       0
Bank Sta=299.9,314.9
XS Rating Curve= 0 ,0
Exp/Cntr=0.3,0.1

Chan Stop Cuts=-1
Use User Specified Reach Order=0